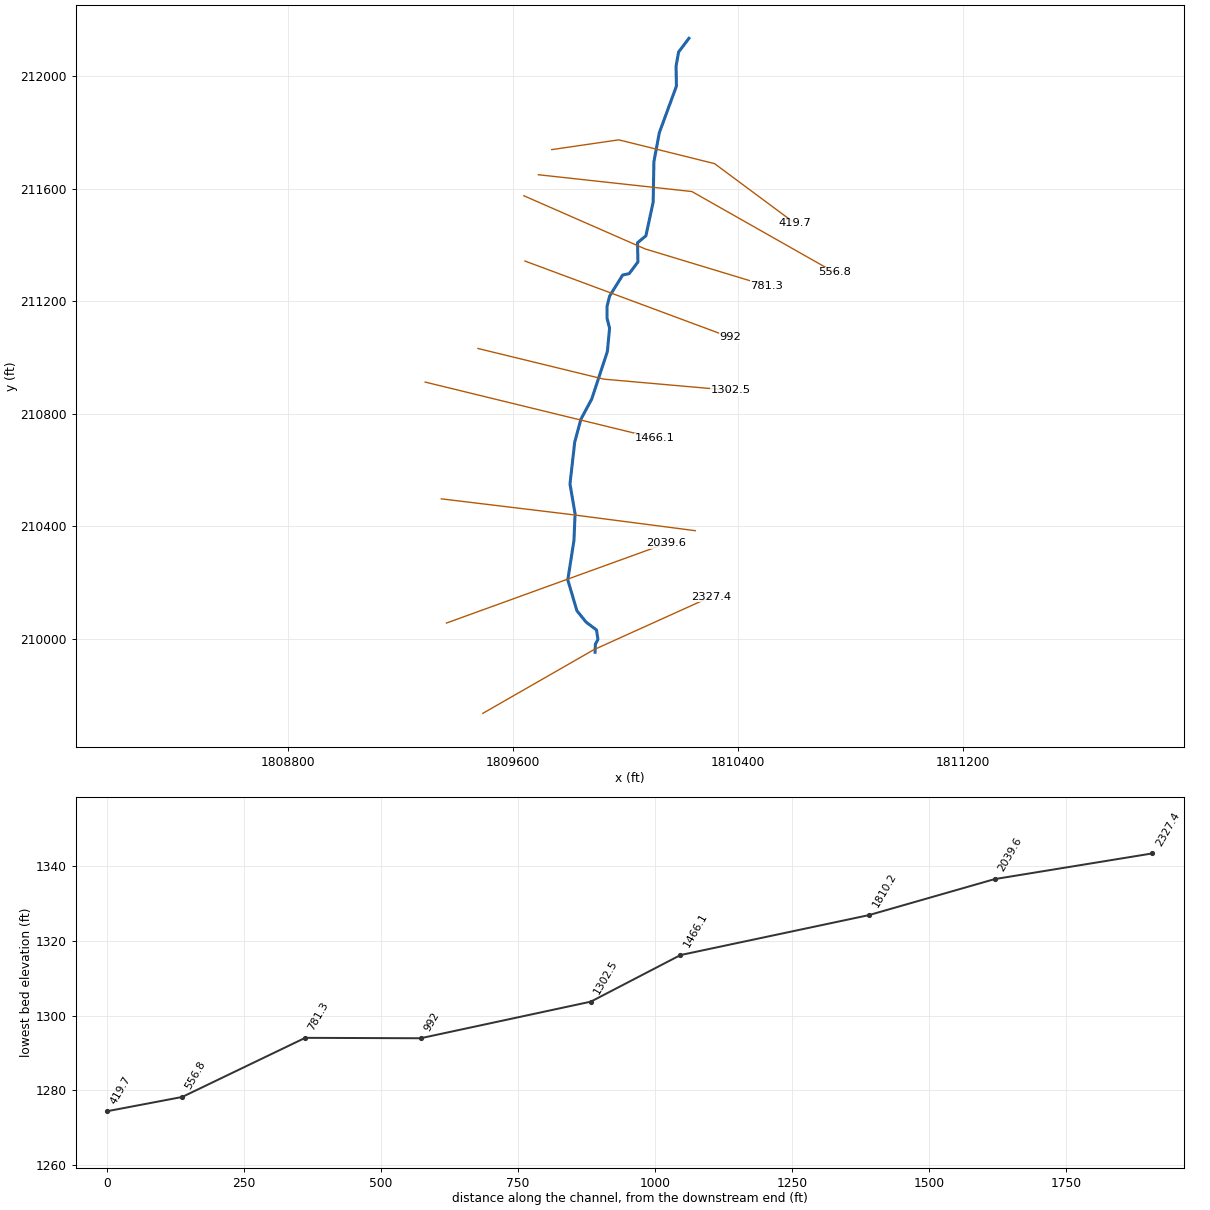
--- RichBr.prj (project) ---

Proj Title=RichBr
Current Plan=p01
Default Exp/Contr=0,0
English Units
Geom File=g01
Flow File=f01
Plan File=p01
BEGIN DESCRIPTION:
END DESCRIPTION:
DSS Export Rating Curves= 0
DSS Export Rating Curve Sorted= 0
DSS Export Volume Flow Curves= 0
DXF OffsetX= 0
DXF OffsetY= 0
DXF ScaleX= 0
DXF ScaleY= 0

--- RichBr.p01 (plan) ---

Plan Title=Floodplain
Program Version=4.00
Geom File=g01
Flow File=f01
K Sum by GR=0
Std Step Tol=0.01
Critical Tol=0.01
Num of Std Step Trials=20
Max Error Tol=0.3
Flow Tol Ratio=0.001
Split Flow NTrial=30
Split Flow Tol=0.02
Split Flow Ratio=0.02
Log Output Level=0
Friction Slope Method=1
Unsteady Friction Slope Method=2
Unsteady Bridges Friction Slope Method=1
Global Log Level=0
CheckData=False
Run HTab=0
Run UNet=0
Run PostProcess=0
UNET Theta=0
UNET Theta Warmup=0
UNET ZTol=0
UNET ZSATol=0
UNET MxIter=0
UNET MaxInSteps=0
UNET DtIC=0
UNET DtMin=0
UNET MaxCRTS=0
UNET WFStab=0
UNET SFStab=0
UNET WFX=0
UNET SFX=0
UNET DSS MLevel=0
UNET DZMax Abort=0
UNET Convert EG Bridges=0
UNET Use Existing IB Tables=0
UNET Froude Limit=0
UNET Froude Power=0
Write IC File=0
Echo Input=False
Echo Output=False
Write Detailed=0

--- RichBr.f01 (steady flow) ---

Flow Title=NFF Regression Equation
Program Version=4.00
Number of Profiles=1
Profile Names=P100yr
River Rch & RM=RichBr,Main      ,2327.4
561.9253
Boundary for River Rch & Prof#=RichBr,Main      ,1
Up Type=0
Dn Type=3
Dn Slope=0.032522

--- RichBr.g01 (geometry) ---

Geom Title=USGS 10m DEM
Program Version=4.00

River Reach=RichBr          ,Main
Reach XY= 30
     1809892.048      209952.633     1809893.161      209981.512
     1809902.297      209998.215      1809897.13        210031.8
      1809859.67      210060.219     1809827.376      210100.263
     1809795.083       210210.06     1809817.042       210350.86
     1809820.917      210445.157     1809802.833       210551.08
     1809819.626       210699.63     1809841.585      210781.009
     1809880.337      210853.347     1809935.882      211022.565
     1809943.633      211105.236      1809934.59      211140.113
      1809934.59       211182.74     1809943.633      211218.909
     1809990.135       211293.83     1810013.387      211298.997
     1810044.388      211340.333     1810043.097      211408.795
     1810072.807      211433.338     1810098.642       211553.47
     1810101.225      211696.853     1810120.601      211800.192
     1810181.313      211965.535     1810180.021       212036.58
     1810189.063      212086.958     1810225.855      212135.625

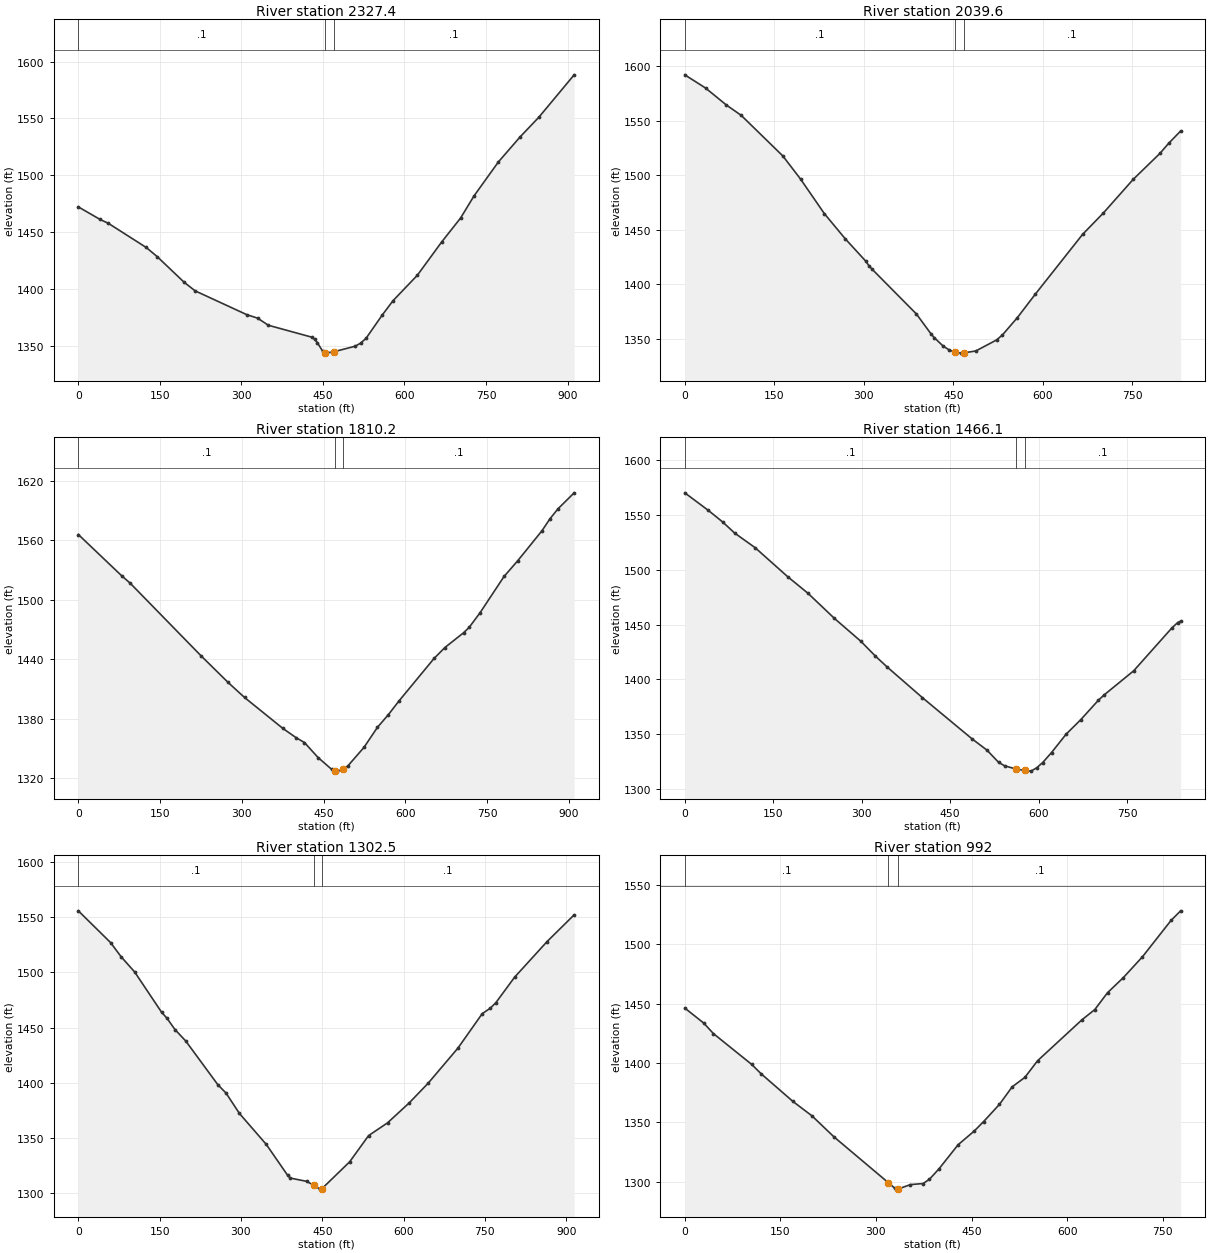
Type RM Length L Ch R = 1 ,2327.4  ,293.8,287.8,286.2
XS GIS Cut Line= 3
     1809492.737      209735.222     1809887.074      209961.309
     1810303.961      210149.864
#Sta/Elev= 30
       0 1472.17      40 1461.14      55 1457.78   124.9 1436.46   144.9 1428.49
   194.8 1405.78   214.8 1398.31   309.7 1377.37   329.7 1374.28   349.6 1368.01
   429.6 1357.51   434.6 1355.73   439.6 1352.74   449.6  1345.1   454.6 1343.49
   454.6  1343.5   469.6 1344.66   509.3 1349.56   519.2 1352.26   529.2 1356.48
     559 1376.97   578.9 1389.63   623.6    1412   668.4 1441.32   703.2  1462.4
   728.1 1481.99   772.8 1511.79   812.6 1533.73   847.4 1551.22   912.1  1588.4
#Mann= 3 , 0 , 0
       0      .1       0   454.6    .045       0   469.6      .1       0
Bank Sta=454.6,469.6
XS Rating Curve= 0 ,0
Exp/Cntr=0.3,0.1

Type RM Length L Ch R = 1 ,2039.6  ,240.8,229.4,217.4
XS GIS Cut Line= 2
     1809363.581      210056.414      1810144.73      210339.381
#Sta/Elev= 30
       0 1591.99    34.8 1579.87    69.6 1564.32    94.5  1554.8   164.2 1517.59
     194  1496.3   233.8 1464.66   268.6 1441.67   303.5 1420.83   308.4 1416.93
   313.4 1413.87     388 1372.58   412.9 1354.02   417.9 1350.86   432.8 1343.11
   442.8  1339.6     452 1337.56   462.7  1336.6     467  1336.8   487.6 1338.58
   522.4 1348.69   532.3 1353.32   557.2 1369.14     587 1390.51   666.6 1445.62
   701.5 1465.28   751.2 1495.97     796 1519.83   810.9 1529.21   830.8 1540.43
#Mann= 3 , 0 , 0
       0      .1       0     452    .045       0     467      .1       0
Bank Sta=452,467
XS Rating Curve= 0 ,0
Exp/Cntr=0.3,0.1

Type RM Length L Ch R = 1 ,1810.2  ,346.5,344,341.6
XS GIS Cut Line= 3
     1809345.379      210498.076     1809797.089      210443.494
     1810248.318      210384.862
#Sta/Elev= 30
       0  1565.8      80 1523.92      95 1516.75     225 1443.48     275 1416.42
     305 1401.32     375 1370.23     400  1360.6     415 1355.84     440 1340.68
   464.9 1328.79   471.3 1327.05   474.8 1326.95   486.3 1328.73   494.6 1332.18
   524.2 1350.87     549 1371.18   568.8 1383.79   588.5 1397.78   652.8 1440.64
   672.6 1451.62   707.2 1466.69   717.1 1471.93   736.9 1486.51   781.4 1523.49
   806.2 1539.16   850.7 1569.41   865.5  1581.6   880.3 1591.72     910 1607.87
#Mann= 3 , 0 , 0
       0      .1       0   471.3    .045       0   486.3      .1       0
Bank Sta=471.3,486.3
XS Rating Curve= 0 ,0
Exp/Cntr=0.3,0.1

Type RM Length L Ch R = 1 ,1466.1  ,163.6,163.6,164.2
XS GIS Cut Line= 2
     1809287.857      210913.287     1810104.876      210714.014
#Sta/Elev= 30
       0 1570.36    39.8 1554.38    64.7 1543.53    84.6 1533.61   119.4 1520.22
   174.2 1493.93     209 1478.61   253.8 1455.69   298.6 1434.81   323.4 1421.22
   343.4 1411.24   403.1 1383.29   487.7 1345.49   512.5 1335.43   532.4 1324.18
   542.4 1321.12   561.6 1318.17   576.6 1316.82   587.2 1316.23   597.1 1319.36
   607.1 1324.09     622 1333.18   646.9 1350.04   671.8 1363.32   701.6 1381.01
   711.6 1385.97   761.4 1407.84     826 1446.87     836 1451.89     841 1453.12
#Mann= 3 , 0 , 0
       0      .1       0   561.6    .045       0   576.6      .1       0
Bank Sta=561.6,576.6
XS Rating Curve= 0 ,0
Exp/Cntr=0.3,0.1

Type RM Length L Ch R = 1 ,1302.5  ,313.2,310.6,307.4
XS GIS Cut Line= 3
     1809475.726      211032.731     1809923.219      210923.707
     1810375.479      210883.829
#Sta/Elev= 30
       0 1555.62    59.4 1526.93    79.2  1513.9     104 1500.22   153.5 1463.88
   163.4 1458.48   178.3 1448.15   198.1 1437.82   257.5 1398.15   272.4 1390.72
   297.2  1372.2   346.7 1344.22   386.3  1316.1   391.2 1313.73     421 1310.78
   434.5 1307.23   445.7 1303.74   449.5 1304.23   500.5 1328.46   535.4 1352.19
   570.3  1363.7   610.3 1381.76   645.2 1399.56   700.1  1431.3     745 1462.52
   759.9 1467.52   769.9 1472.31   804.8 1495.58   864.7 1527.84   914.6 1551.99
#Mann= 3 , 0 , 0
       0      .1       0   434.5    .045       0   449.5      .1       0
Bank Sta=434.5,449.5
XS Rating Curve= 0 ,0
Exp/Cntr=0.3,0.1

Type RM Length L Ch R = 1 ,992     ,213.6,210.6,217.1
XS GIS Cut Line= 2
     1809642.563      211343.716     1810371.901      211072.705
#Sta/Elev= 30
       0 1446.26    29.9 1433.55    44.9 1424.77   104.7 1398.98   119.7 1391.01
   169.6 1367.75   199.5  1355.6   234.4 1337.75   319.5 1299.32   329.2 1294.85
   334.2 1293.93   334.5 1293.98   354.1 1297.74   374.1 1298.64     384 1302.28
     399 1311.06   428.9 1331.28   453.9 1342.64   468.8 1350.68   493.8 1365.26
   513.7 1379.96   533.7 1387.95   553.6 1401.94   623.4 1436.46   643.4 1444.98
   663.4 1459.18   688.3 1471.93   718.2  1489.4   763.1 1520.02   778.1 1528.06
#Mann= 3 , 0 , 0
       0      .1       0   319.5    .045       0   334.5      .1       0
Bank Sta=319.5,334.5
XS Rating Curve= 0 ,0
Exp/Cntr=0.3,0.1

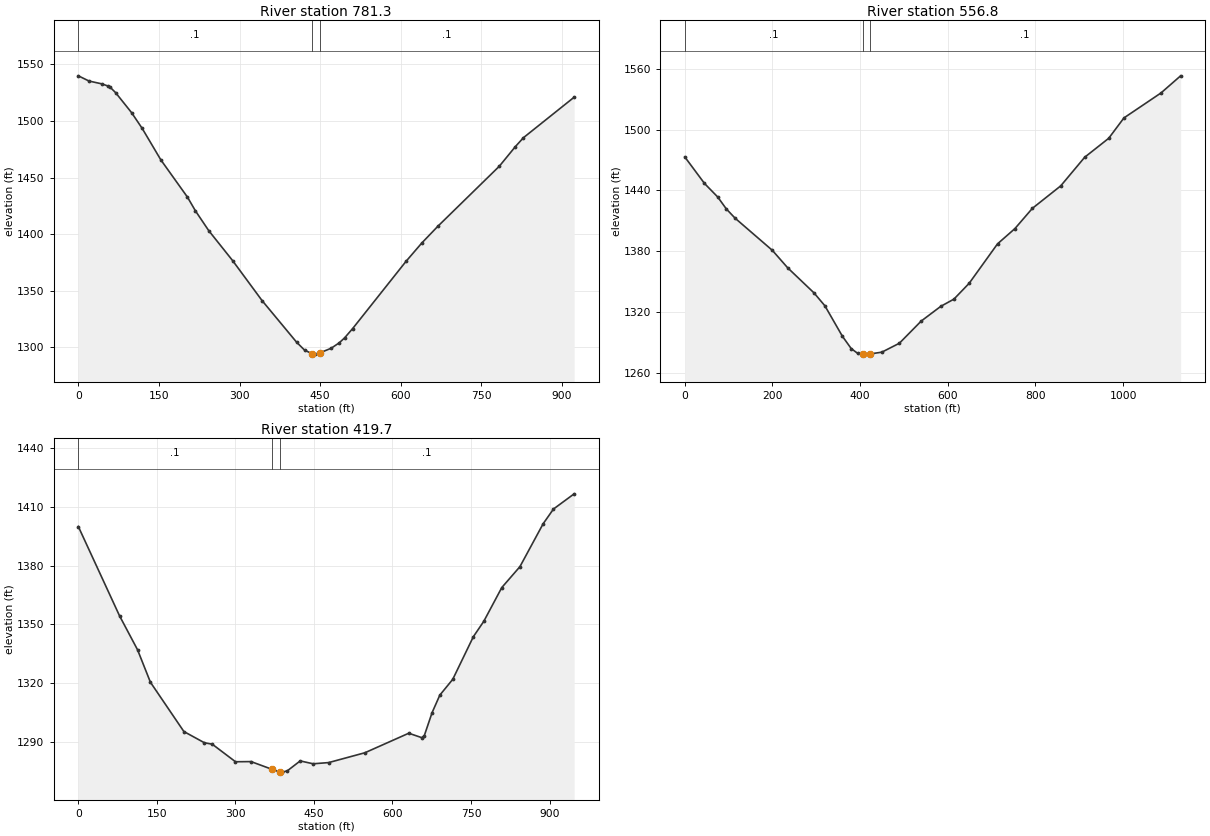
Type RM Length L Ch R = 1 ,781.3   ,217.3,224.5,231.7
XS GIS Cut Line= 3
     1809638.971       211575.79     1810069.903      211386.865
     1810502.542      211255.625
#Sta/Elev= 30
       0 1539.91    19.8 1535.32    44.6 1532.71    54.5 1530.98    59.4 1529.73
    69.3 1525.08    99.1 1507.37   118.9  1493.4   153.5 1465.68   203.1 1432.72
   217.9 1420.62   242.7 1403.11   287.3 1376.54   341.8 1341.39   406.1 1304.59
     421 1297.56   434.9 1294.45   440.8 1294.04   449.9 1295.27   470.5 1299.24
   485.4    1304   495.4 1308.37   510.3 1316.54   609.6 1375.92   639.4 1392.37
   669.2  1407.1   783.5 1460.12   813.3 1477.42   828.2 1485.23   922.6 1521.03
#Mann= 3 , 0 , 0
       0      .1       0   434.9    .045       0   449.9      .1       0
Bank Sta=434.9,449.9
XS Rating Curve= 0 ,0
Exp/Cntr=0.3,0.1

Type RM Length L Ch R = 1 ,556.8   ,140.2,137.1,134.1
XS GIS Cut Line= 3
     1809690.388      211650.596     1810236.396      211590.814
     1810742.548      211303.861
#Sta/Elev= 30
       0 1473.16    44.9 1446.94    74.9 1433.63    94.9 1421.66   114.8 1412.57
   199.7 1380.81   234.7 1363.52   294.6 1338.79   319.6 1325.96   359.5 1295.86
   379.5 1283.74   394.5 1278.88   406.7 1278.54   414.4 1278.18   421.7 1278.32
   449.4  1280.1   489.4 1288.91   539.3 1310.87   584.1 1325.47   613.9 1332.54
   648.7  1348.2   713.4  1387.2   753.2 1402.34   792.9 1422.31   857.6 1444.54
   912.3 1472.86     967 1491.56  1001.8 1511.72  1086.4 1536.43  1131.1 1553.34
#Mann= 3 , 0 , 0
       0      .1       0   406.7    .045       0   421.7      .1       0
Bank Sta=406.7,421.7
XS Rating Curve= 0 ,0
Exp/Cntr=0.3,0.1

Type RM Length L Ch R = 1 ,419.7   ,428.9,419.7,410.4
XS GIS Cut Line= 4
     1809737.982      211739.894     1809976.393      211774.711
     1810316.857      211690.087     1810602.224      211478.347
#Sta/Elev= 30
       0 1400.05    78.7 1354.36   113.1 1336.98   137.7 1320.37   201.6 1295.14
   240.9 1289.38   255.8 1288.66   300.2 1279.67   329.9 1279.75   369.8 1275.82
   384.8 1274.41   389.2 1274.36   399.1    1275   423.8  1280.1   448.5 1278.63
   478.1 1279.24   547.3 1284.27   631.2 1294.27   655.9 1292.01   660.9 1293.08
   675.7 1304.79   690.5 1313.77   715.2 1321.86   754.6  1343.7   774.4 1351.51
   808.9 1368.84   843.5 1379.52   887.9  1401.5   907.6 1409.02   947.1  1416.8
#Mann= 3 , 0 , 0
       0      .1       0   369.8    .045       0   384.8      .1       0
Bank Sta=369.8,384.8
XS Rating Curve= 0 ,0
Exp/Cntr=0.3,0.1

Chan Stop Cuts=-1
Use User Specified Reach Order=0